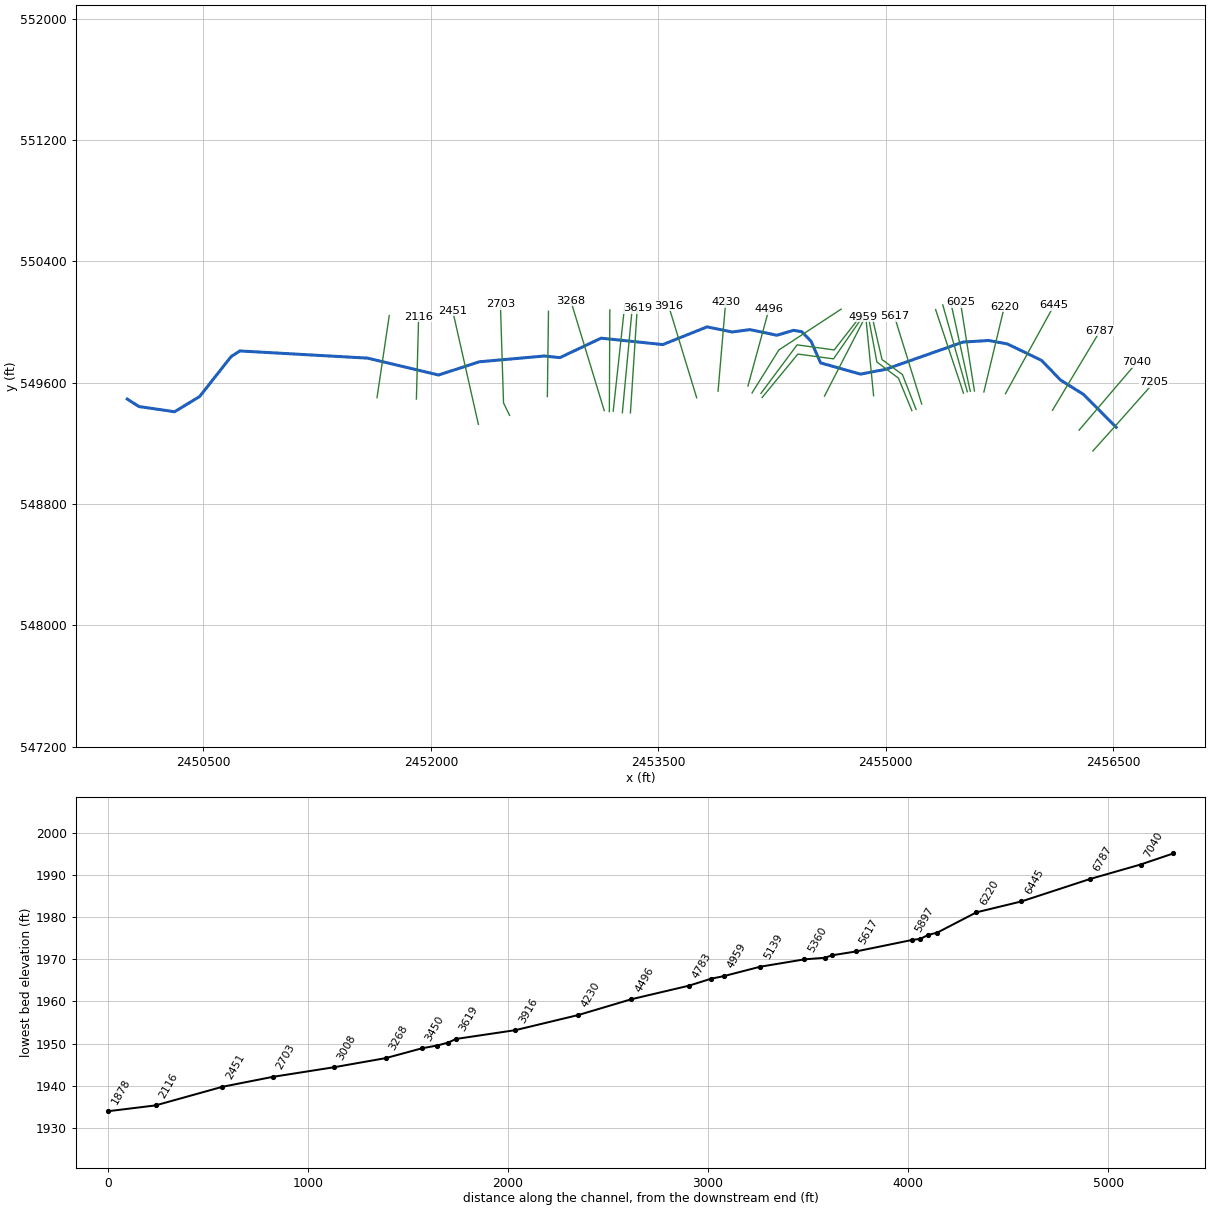
--- LSTONYRN.prj (project) ---

Proj Title=LSTONYRN
Current Plan=p01
Default Exp/Contr=0,0
English Units
Geom File=g01
Flow File=f01
Plan File=p01
BEGIN DESCRIPTION:
Stream Name: Little Stony Run
Flood Zone: Approximate
Pendleton County, West Virginia
HEC-RAS Version: 5.0.7
Hydrology Method:
Regression equation
END DESCRIPTION:
DSS Export Rating Curves= 0
DSS Export Rating Curve Sorted= 0
DSS Export Volume Flow Curves= 0
DXF OffsetX= 0
DXF OffsetY= 0
DXF ScaleX= 0
DXF ScaleY= 0

--- LSTONYRN.p01 (plan) ---

Plan Title=Floodplain
Program Version=5.07
Short Identifier=Floodplain
Geom File=g01
Flow File=f01
Subcritical Flow
K Sum by GR= 0
Std Step Tol= 0.01
Critical Tol= 0.01
Num of Std Step Trials= 20
Max Error Tol= 0.3
Flow Tol Ratio= 0.001
Split Flow NTrial= 30
Split Flow Tol= 0.02
Split Flow Ratio= 0.02
Log Output Level= 0
Friction Slope Method= 1
Unsteady Friction Slope Method= 2
Unsteady Bridges Friction Slope Method= 1
Parabolic Critical Depth
Global Vel Dist= 0 , 0 , 0
Global Log Level= 0
CheckData=True
Encroach Param=-1 ,0,0, 0
Mapping Interval=1HOUR
Computation Time Step Use Courant=        0
Computation Time Step Use Time Series=    0
Computation Time Step Count To Double=0
Computation Time Step Max Doubling=0
Computation Time Step Max Halving=0
Computation Time Step Residence Courant=0
Run HTab= 0
Run UNet= 0
Run Sediment= 0
Run PostProcess= 0
Run WQNet= 0
Run RASMapper= 0
UNET Theta= 0
UNET Theta Warmup= 0
UNET ZTol= 0
UNET ZSATol= 0
UNET MxIter= 0
UNET Max Iter WO Improvement= 0
UNET MaxInSteps= 0
UNET DtIC= 0
UNET DtMin= 0
UNET MaxCRTS= 0
UNET WFStab= 0
UNET SFStab= 0
UNET WFX= 1
UNET SFX= 1
UNET 1D Methodology=Finite Difference
UNET DSS MLevel= 1
UNET Pardiso=0
UNET DZMax Abort= 0
UNET Use Existing IB Tables= 0
UNET Froude Reduction=False
UNET Froude Limit= 0
UNET Froude Power= 0
UNET D1 Cores= 0
UNET D2 Coriolis=0
UNET D2 Cores= 0
UNET D2 Theta= 1
UNET D2 Theta Warmup= 1
UNET D2 Z Tol= 0.01
UNET D2 Volume Tol= 0.01
UNET D2 Max Iterations= 20
UNET D2 Equation= 0
UNET D2 RampUpFraction=0.1
UNET D2 TimeSlices= 1
UNET D2 BCVolumeCheck=0
UNET D1D2 MaxIter= 0
UNET D1D2 ZTol=0.01
UNET D1D2 QTol=0.1
UNET D1D2 MinQTol=1
Write IC File= 0
Write IC File at Fixed DateTime=0
Write IC File at Sim End=0
Echo Input=False
Echo Parameters=False
Echo Output=False
Write Detailed= 0
HDF Write Warmup=0
HDF Write Time Slices=0
HDF Flush=0
HDF Face Node Velocities=0
HDF Compression= 1
HDF Chunk Size= 1
HDF Spatial Parts= 1
HDF Use Max Rows=0
HDF Fixed Rows= 1
Calibration Method= 0
Calibration Iterations= 20
Calibration Max Change=0.05
Calibration Tolerance=0.2
Calibration Maximum=1.5
Calibration Minimum=0.5
Calibration Optimization Method= 1
WQ AD Non Conservative
WQ ULTIMATE=-1
WQ Max Comp Step=1HOUR
WQ Output Interval=15MIN
WQ Output Selected Increments= 0
WQ Output face flow=0
WQ Output face velocity=0
WQ Output face area=0
WQ Output face dispersion=0
WQ Output cell volume=0
WQ Output cell surface area=0
WQ Output cell continuity=0
WQ Output cumulative cell continuity=0
WQ Output face conc=0
WQ Output face dconc_dx=0
WQ Output face courant=0
WQ Output face peclet=0
WQ Output face adv mass=0
WQ Output face disp mass=0
WQ Output cell mass=0
WQ Output cell source sink temp=0
WQ Output nsm pathways=0
WQ Output nsm derived pathways=0
WQ Output MaxMinRange=-1
WQ Daily Max Min Mean=-1
WQ Daily Range=0
WQ Daily Time=0
WQ Create Restart=0
WQ Fixed Restart=0
WQ System Summary=0
WQ Write To DSS=0
WQ Use Fixed Temperature=0
Sorting and Armoring Iterations= 10
XS Update Threshold= 0.02
Bed Roughness Predictor= 0
Hydraulics Update Threshold= 0.02
Energy Slope Method= 1
Volume Change Method= 1
Sediment Retention Method= 0
XS Weighting Method= 0
Number of US Weighted Cross Sections= 1
Number of DS Weighted Cross Sections= 1
Upstream XS Weight=0
Main XS Weight=1
Downstream XS Weight=0
Number of DS XS's Weighted with US Boundary= 1
Upstream Boundary Weight= 1
Weight of XSs Associated with US Boundary= 0
Number of US XS's Weighted with DS Boundary= 1
Downstream Boundary Weight= 0.5
Weight of XSs Associated with DS Boundary= 0.5
Percentile Method= 0
Sediment Output Level= 3
Mass or Volume Output= 0
Output Increment Type= 1
Profile and TS Output Increment= 1
XS Output Flag= 0
XS Output Increment= 10
Write Gradation File= 0
Read Gradation Hotstart= 0
Write HDF5 File= 1
Write Binary Output= 1
Write DSS Sediment File= 0
SV Curve= 0
Specific Gage Flag= 0

--- LSTONYRN.f01 (steady flow) ---

Flow Title=Flows
Program Version=5.07
Number of Profiles= 6
Profile Names=P100yr,P10yr,P25yr,P50yr,P500yr,P101yr
River Rch & RM=LSTONYRN,Main            ,7205
     515     241     341     425     754     626
River Rch & RM=LSTONYRN,Main            ,6787
     584     273     386     482     856     711
River Rch & RM=LSTONYRN,Main            ,5360
     709     331     468     585    1042     863
River Rch & RM=LSTONYRN,Main            ,4496
     795     370     524     656    1169     967
Boundary for River Rch & Prof#=LSTONYRN,Main            , 1
Up Type= 0
Dn Type= 3
Dn Slope=0.01516
Boundary for River Rch & Prof#=LSTONYRN,Main            , 2
Up Type= 0
Dn Type= 3
Dn Slope=0.01516
Boundary for River Rch & Prof#=LSTONYRN,Main            , 3
Up Type= 0
Dn Type= 3
Dn Slope=0.01516
Boundary for River Rch & Prof#=LSTONYRN,Main            , 4
Up Type= 0
Dn Type= 3
Dn Slope=0.01516
Boundary for River Rch & Prof#=LSTONYRN,Main            , 5
Up Type= 0
Dn Type= 3
Dn Slope=0.01516
Boundary for River Rch & Prof#=LSTONYRN,Main            , 6
Up Type= 0
Dn Type= 3
Dn Slope=0.01516
DSS Import GetInterval= 0
DSS Import GetPeak= 0
DSS Import FillOption= 0

--- LSTONYRN.g01 (geometry) ---

Geom Title=Geometry
Program Version=5.07

River Reach=LSTONYRN        ,Main
Reach XY= 30
     2456518.257      549306.415     2456303.836      549522.559
     2456151.705       549617.56     2456026.246      549747.469
     2455801.631      549855.565     2455678.088      549878.605
     2455508.095      549868.076     2454996.693      549687.963
     2454832.535      549656.837     2454569.706      549730.733
     2454507.169      549872.655      2454444.82      549936.846
     2454391.035       549945.52     2454282.072      549913.141
      2454103.41      549950.337     2453986.827      549934.416
     2453821.173      549968.331     2453529.379      549851.587
     2453122.538      549893.804     2452851.063      549765.559
     2452747.869      549776.162     2452319.674       549738.11
     2452051.057      549650.926     2451582.808      549762.233
2450740.65720172 549809.543660732450683.33515311549772.423165336
2450475.56275358549508.911450993 2450310.7053891549408.780150181
2450075.79720456549442.9643497752449998.67131485549492.110935464

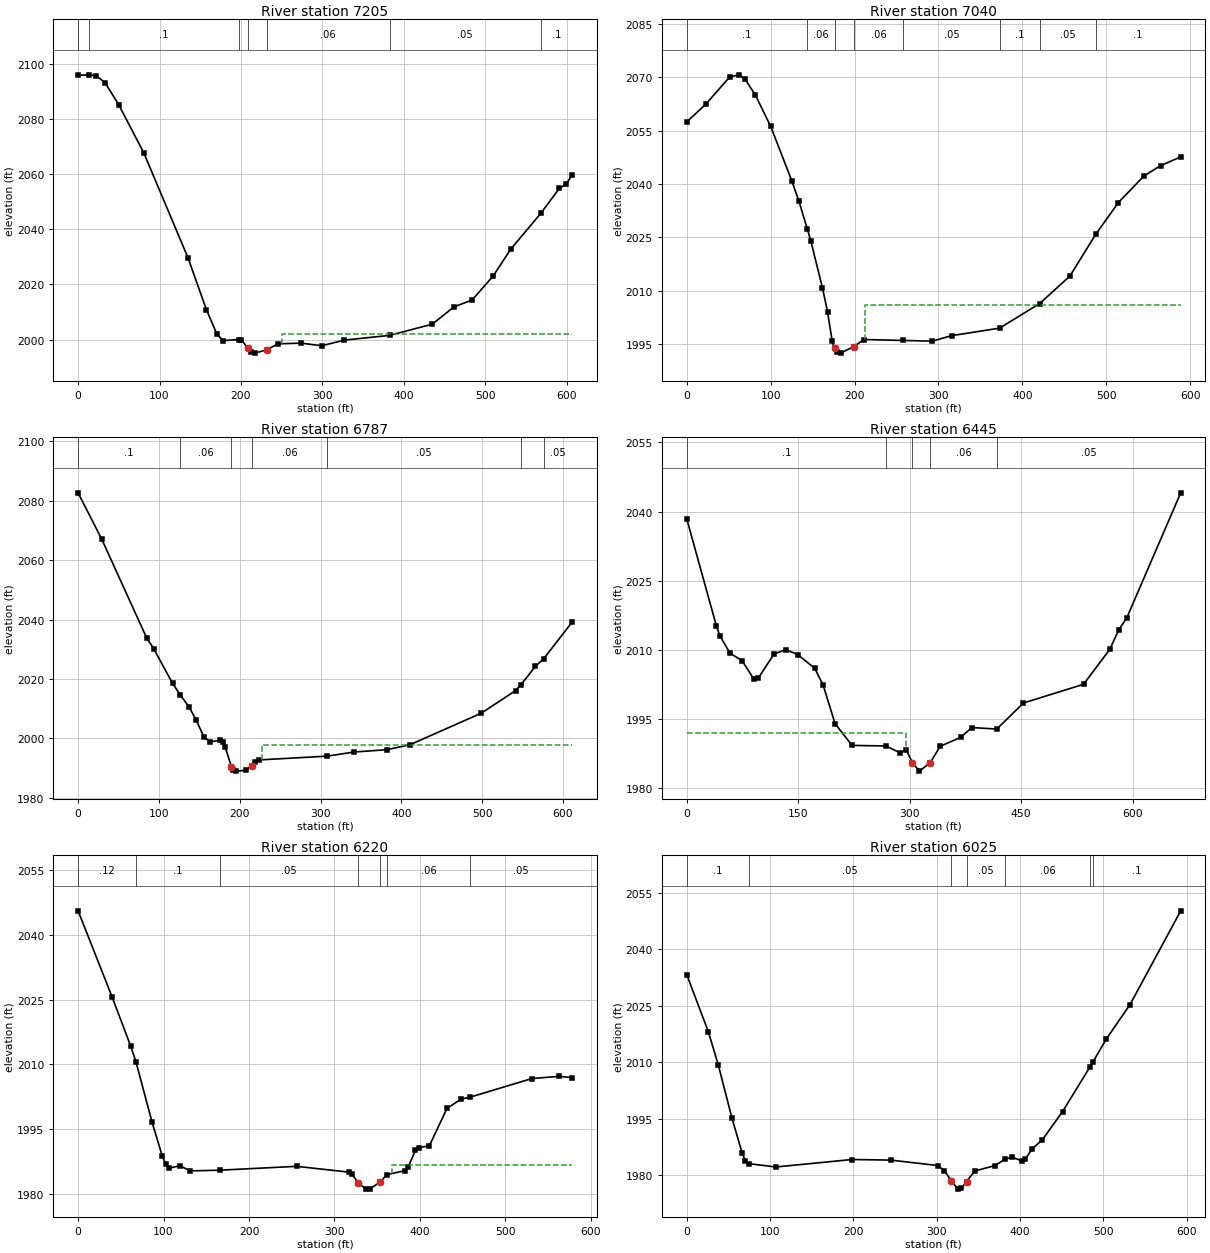
Type RM Length L Ch R = 1 ,7205    ,164.3,164.6,165
XS GIS Cut Line= 3
2456364.88631129549150.274393223     2456510.736      549313.005
2456768.19686887549603.291098387
#Sta/Elev= 30
       0 2095.85   13.082096.037    22.3 2095.73    33.1 2093.17    49.9  2085.2
    80.7  2067.7   134.9 2029.71   157.5 2010.91   170.6  2001.9   178.1 1999.66
  197.132000.039   200.6 1999.95   208.5 1996.87   212.5 1995.41     217 1995.11
   231.7 1996.32   245.4 1998.48   273.7 1998.73   299.2  1997.8     327 1999.83
  382.512001.544   434.9 2005.61   461.6 2011.89   483.8 2014.37   509.8 2023.12
   531.1 2032.74  568.072045.761   591.1  2054.9   599.6 2056.33   606.5 2059.81
#Mann= 7 ,-1 , 0
       0      .1       0   13.08      .1       0  197.13     .06       0
   208.5    .045       0   231.7     .06       0  382.51     .05       0
  568.07      .1       0
#XS Ineff= 2 , 0
                          250.94         2002.18
Permanent Ineff=
       F       F
Bank Sta=208.5,231.7
XS Rating Curve= 0 ,0
Exp/Cntr=0.3,0.1

Type RM Length L Ch R = 1 ,7040    ,250.7,253.8,256.4
XS GIS Cut Line= 2
2456273.82014725 549287.448491612456655.96434436 549735.44188516
#Sta/Elev= 30
       0 2057.45      23 2062.52    51.3 2070.13    62.4 2070.67    69.2 2069.51
    81.6 2065.04     100 2056.16   125.1 2040.91   133.6 2035.17  143.712027.309
   147.8 2024.01   161.7  2010.8   167.7 2004.13   173.3 1995.84   176.2 1993.81
     179 1992.81   183.3 1992.47   198.9 1994.29     211 1996.29  258.261996.035
   292.5 1995.83   315.8 1997.39  372.811999.486  420.612006.399   456.7 2014.12
  487.362025.819   514.5 2034.78     545 2042.26   564.9 2045.16   588.8 2047.61
#Mann= 8 ,-1 , 0
       0      .1       0  143.71     .06       0   176.2    .045       0
   198.9     .06       0  258.26     .05       0  372.81      .1       0
  420.61     .05       0  487.36      .1       0
#XS Ineff= 2 , 0
                          212.37         2005.88
Permanent Ineff=
       F       F
Bank Sta=176.2,198.9
XS Rating Curve= 0 ,0
Exp/Cntr=0.3,0.1

Type RM Length L Ch R = 1 ,6787    ,341,341.2,341.9
XS GIS Cut Line= 2
2456098.57981951549418.731196448        2456413.      549942.786
#Sta/Elev= 30
       0  2082.6    29.4 2066.91    84.8 2033.83    93.5 2030.22   116.8 2018.56
  126.362014.633   137.3 2010.58     146 2006.27   155.8 2000.43   163.6 1998.93
   175.2 1999.33   179.1 1998.79   182.1    1997   189.7 1990.53   191.4 1989.51
   195.6 1989.02   207.2 1989.26   214.8 1990.76   219.4 1992.23   224.1 1992.79
  308.33 1994.06   341.3 1995.44   382.2 1996.23   410.7 1997.91   498.8 2008.49
   541.3  2016.1   547.52017.924   565.8 2024.23  576.332026.891   611.1 2039.09
#Mann= 7 ,-1 , 0
       0      .1       0  126.36     .06       0   189.7    .045       0
   214.8     .06       0  308.33     .05       0   547.5      .1       0
  576.33     .05       0
#XS Ineff= 2 , 0
                           227.1         1997.84
Permanent Ineff=
       F       F
Bank Sta=189.7,214.8
XS Rating Curve= 0 ,0
Exp/Cntr=0.3,0.1

Type RM Length L Ch R = 1 ,6445    ,221.4,225.4,230.4
XS GIS Cut Line= 2
2455788.53516387549527.9500982242456108.72055742550110.513475485
#Sta/Elev= 30
       0 2038.36    39.9 2015.13    44.4 2013.09    58.1  2009.3    74.5 2007.64
    90.1  2003.7    95.9 2003.83   117.5 2009.15   133.4 2010.07   149.4 2008.98
   172.2 2006.01   183.5 2002.36   199.6 1993.99   222.4  1989.3  267.861989.174
   286.3 1987.75   295.5 1988.27   303.6 1985.57   313.1 1983.72   327.4 1985.51
   341.1  1989.1   368.5 1991.05   383.8 1993.17  417.22 1992.84     453 1998.49
     534 2002.55   569.4 2010.14   581.1 2014.28   592.2 2016.96   664.8 2044.07
#Mann= 5 ,-1 , 0
       0      .1       0  267.86     .06       0   303.6    .045       0
   327.4     .06       0  417.22     .05       0
#XS Ineff= 2 , 0
          295.59 1992.04
Permanent Ineff=
       F       F
Bank Sta=303.6,327.4
XS Rating Curve= 0 ,0
Exp/Cntr=0.3,0.1

Type RM Length L Ch R = 1 ,6220    ,188,194.6,201.1
XS GIS Cut Line= 2
2455646.21859016549539.1857867732455781.04915906550101.171052429
#Sta/Elev= 30
       0 2045.59      40 2025.52    61.4 2014.32   67.672010.639    86.4 1996.73
    98.4 1988.82   102.5 1986.95   106.6    1986     119 1986.53   131.3 1985.36
  165.521985.513   255.6 1986.41   316.4 1985.08   320.6 1984.54     328 1982.53
     337 1981.13   341.1 1981.18   353.5 1982.76  361.221984.478   382.3  1985.4
   386.4 1986.34   394.6 1990.08   398.7 1990.72     411 1991.17   431.6 1999.83
   448.1 2001.97  459.072002.453     531 2006.75   563.2 2007.25   577.9 2006.94
#Mann= 7 ,-1 , 0
       0     .12       0   67.67      .1       0  165.52     .05       0
     328    .045       0   353.5     .05       0  361.22     .06       0
  459.07     .05       0
#XS Ineff= 2 , 0
                          366.96         1986.68
Permanent Ineff=
       F       F
Bank Sta=328,353.5
XS Rating Curve= 0 ,0
Exp/Cntr=0.3,0.1

Type RM Length L Ch R = 1 ,6025    ,46.1,47.1,47.8
XS GIS Cut Line= 2
2455583.89640772549545.4108665142455491.62983433550131.021158879
#Sta/Elev= 30
       0 2033.21    25.8 2018.13    37.9 2009.19    54.1 1995.24    66.3 1985.99
    70.3 1983.79   74.411983.101   106.8 1982.22   198.2  1984.2   244.5 1984.05
   301.1 1982.61   309.2 1981.24   317.6 1978.51   325.4 1976.34   329.5 1976.56
   335.71978.334   345.7 1981.16     370  1982.6  381.671984.269   390.2 1984.83
   402.4 1983.81   406.4 1984.36   414.5 1987.05   426.7 1989.42     451 1996.94
  484.092008.842  487.422010.088   503.6 2016.23     532 2025.35   592.8 2050.22
#Mann= 7 ,-1 , 0
       0      .1       0   74.41     .05       0   317.6    .045       0
   335.7     .05       0  381.67     .06       0  484.09     .05       0
  487.42      .1       0
Bank Sta=317.6,335.7
XS Rating Curve= 0 ,0
Exp/Cntr(USF)=0,0
Exp/Cntr=0.5,0.3

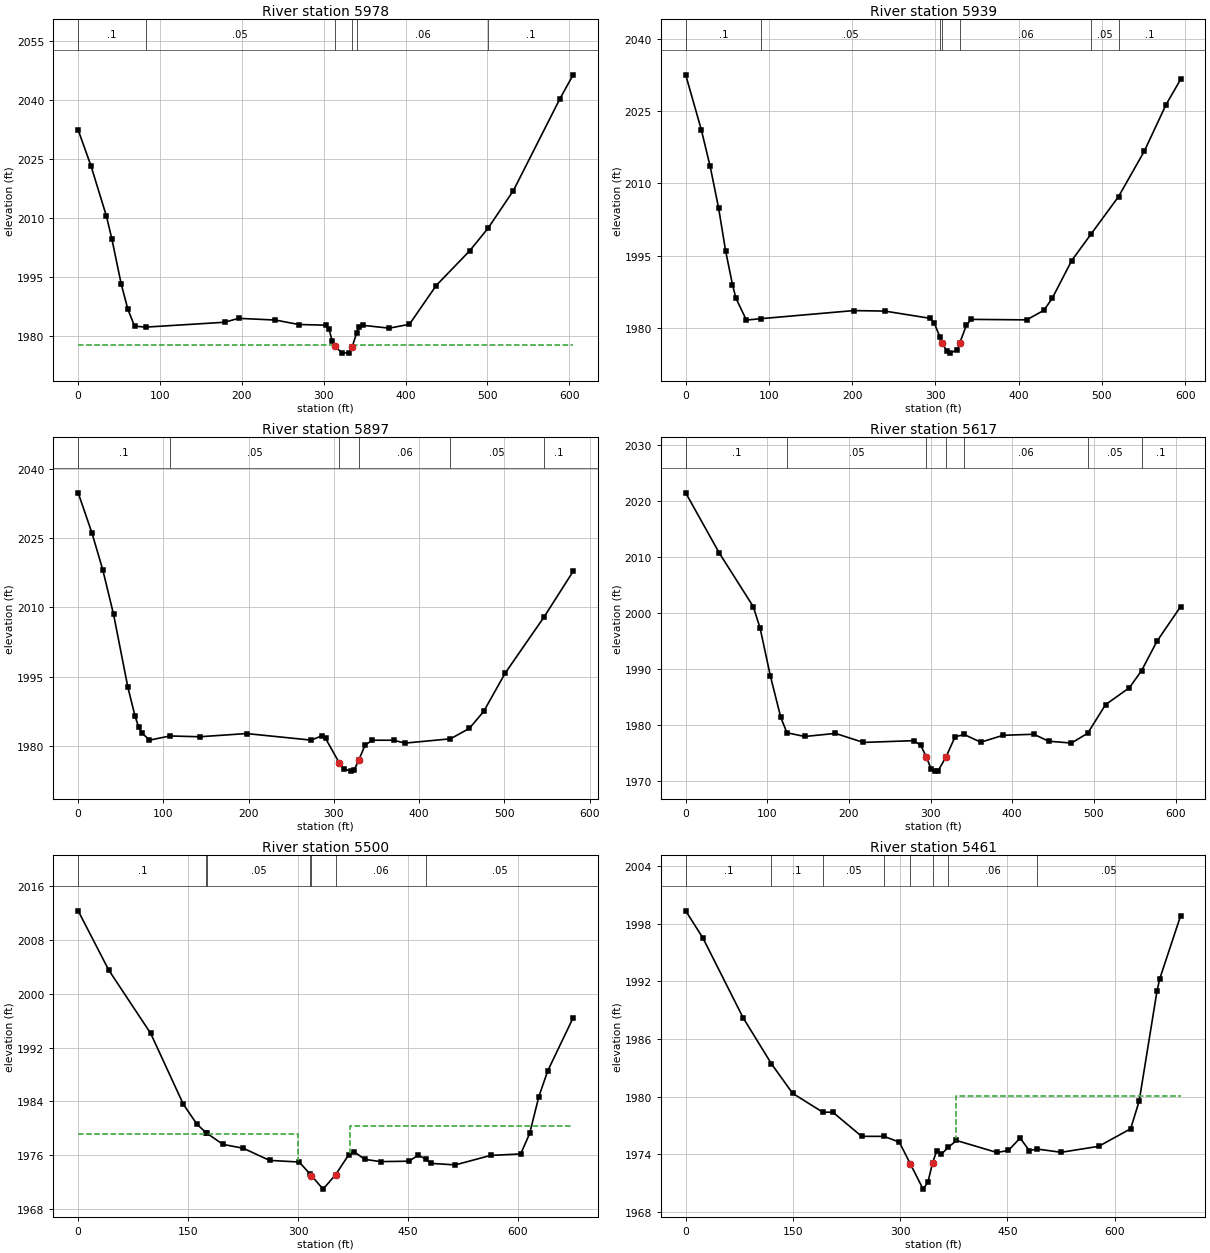
Type RM Length L Ch R = 1 ,5978    ,37.9,39.1,39.8
XS GIS Cut Line= 2
2455556.47969283549543.5880359642455426.83574225550134.188255257
#Sta/Elev= 30
       0 2032.34    15.7  2023.2    34.5  2010.5    41.2 2004.67    52.5 1993.34
    60.7 1986.87    68.9 1982.59   82.451982.334   178.9 1983.57   195.9 1984.56
   240.9 1984.13   269.5    1983   302.3 1982.83   306.5 1981.77   310.5 1978.69
   313.2 1977.49   322.8 1975.74     331 1975.87   334.81977.358  340.171980.841
   343.3 1982.33   347.4  1982.8   380.1 1982.07   404.7 1983.05   437.4 1992.89
   478.4 2001.71   500.9 2007.46   531.7 2016.96   588.5 2040.23   604.7 2046.32
#Mann= 6 ,-1 , 0
       0      .1       0   82.45     .05       0   313.2    .045       0
   334.8     .05       0  340.17     .06       0   500.9      .1       0
#XS Ineff= 2 , 0
          312.61 1977.87  335.19         1977.87
Permanent Ineff=
       F       F
Bank Sta=313.2,334.8
XS Rating Curve= 0 ,0
Exp/Cntr(USF)=0,0
Exp/Cntr=0.5,0.3

Type RM Length L Ch R = 1 ,5939    ,41.1,42.2,42.5
XS GIS Cut Line= 2
2455536.90909562549540.7618218112455375.27685922550112.939146832
#Sta/Elev= 30
       0 2032.48    18.8 2021.08    29.4  2013.5    39.6 2004.84    47.9 1996.07
    56.2 1989.02    60.4 1986.19    72.9 1981.69   90.911981.984   201.7 1983.65
   239.1 1983.55   293.2 1982.06   298.4 1981.14  305.441978.151   308.1 1976.88
     314 1975.25   318.1 1974.84   326.4 1975.57   329.41977.026   337.3 1980.66
     343 1981.83   409.6 1981.73   430.3 1983.71   440.2 1986.16   463.7 1994.01
  486.841999.474  519.972007.259   550.9 2016.66   577.1 2026.33   594.6 2031.55
#Mann= 7 ,-1 , 0
       0      .1       0   90.91     .05       0  305.44     .06       0
   308.1    .045       0   329.4     .06       0  486.84     .05       0
  519.97      .1       0
Bank Sta=308.1,329.4
XS Rating Curve= 0 ,0
Exp/Cntr=0.5,0.3

Type RM Length L Ch R = 1 ,5897    ,280.1,279.8,279.5
XS GIS Cut Line= 2
2455511.55188222549531.5614655482455327.96023107550082.336418978
#Sta/Elev= 30
       0 2034.79    16.2 2026.08    28.8 2018.17    41.5 2008.51    58.3 1992.71
    66.8  1986.4      71 1984.07    75.2 1982.77    83.6 1981.26   107.6 1982.17
   142.6    1982   197.5 1982.69   273.4 1981.27     286 1982.22   290.2 1981.63
   306.1 1976.41   311.3 1975.07   319.7 1974.56     324 1974.89     329 1976.91
   336.6 1980.19     345 1981.25   370.3 1981.25     383 1980.62  436.741981.555
   458.9 1983.81   475.7 1987.49     501  1995.8  546.452007.906   580.6  2017.8
#Mann= 6 ,-1 , 0
       0      .1       0   107.6     .05       0   306.1    .045       0
     329     .06       0  436.74     .05       0  546.45      .1       0
Bank Sta=306.1,329
XS Rating Curve= 0 ,0
Exp/Cntr(USF)=0,0
Exp/Cntr=0.3,0.1

Type RM Length L Ch R = 1 ,5617    ,104.8,117.1,131
XS GIS Cut Line= 2
2455236.20275407549459.7947567012455056.00117866550038.701077245
#Sta/Elev= 30
       0  2021.5    40.9 2010.82    82.8 2001.19    91.2 1997.32   103.8 1988.77
   116.4 1981.47  123.951978.695   145.7 1978.02   183.4 1978.57   217.7 1976.96
   279.7 1977.28     288 1976.42   294.5 1974.45   300.5 1972.28   304.9 1971.84
   309.1 1971.87   318.8 1974.36     330 1977.96  341.181978.376   361.4    1977
   388.7 1978.23   426.4 1978.42   444.5 1977.18   472.4 1976.85   492.4  1978.6
   514.3  1983.7   543.6 1986.74  558.421989.773   577.2    1995   606.3 2001.21
#Mann= 7 ,-1 , 0
       0      .1       0  123.95     .05       0   294.5    .045       0
   318.8     .05       0  341.18     .06       0   492.4     .05       0
  558.42      .1       0
Bank Sta=294.5,318.8
XS Rating Curve= 0 ,0
Exp/Cntr=0.5,0.3

Type RM Length L Ch R = 1 ,5500    ,38.1,38.8,37.6
XS GIS Cut Line= 4
2455198.80606656549424.9012802692455109.26983054549653.694137418
 2454974.7301026549752.5417653852454915.41587684550008.628581337
#Sta/Elev= 30
       0 2012.32    41.7 2003.52      99 1994.09   143.6 1983.55   162.1  1980.6
  175.051979.298   175.31979.278   197.7  1977.6   225.5 1977.02   261.2 1975.22
   301.8 1974.98  316.881973.126   318.3 1972.97   334.2 1970.95   351.4  1973.1
   369.3 1976.07   376.1 1976.53   391.4 1975.37   412.6 1975.04   451.3  1975.1
   464.3    1976  474.271975.414   481.3 1974.78   514.6 1974.55   562.9 1975.96
   603.9 1976.18   616.2 1979.23   628.6 1984.67   640.9 1988.55   675.5 1996.42
#Mann= 7 ,-1 , 0
       0      .1       0  175.05      .1       0   175.3     .05       0
  316.88      .1       0   318.3    .045       0   351.4     .06       0
  474.27     .05       0
#XS Ineff= 2 , 0
          300.61 1979.16  371.17         1980.29
Permanent Ineff=
       F       F
Bank Sta=318.3,351.4
XS Rating Curve= 0 ,0
Exp/Cntr(USF)=0,0
Exp/Cntr=0.5,0.3

Type RM Length L Ch R = 1 ,5461    ,119,101.4,85.5
XS GIS Cut Line= 4
2455171.07823119549416.7086502442455082.79821828549630.325328831
2454940.71785305549736.8590793882454888.39251598550015.617515857
#Sta/Elev= 30
       0 1999.36      24 1996.54    80.3 1988.22  120.031983.406   149.5 1980.34
  191.741978.371   205.8 1978.37   246.2 1975.85  277.421975.852   298.8 1975.25
   314.4 1972.96   332.1 1970.35   338.8 1971.07   345.4  1973.1   351.2 1974.36
   357.3 1973.96  366.991974.692   378.8 1975.42   435.2 1974.17   451.5 1974.38
   467.8 1975.68   480.7 1974.36  491.361974.532   525.2 1974.19   577.7 1974.81
   622.4 1976.64   634.3 1979.51   659.3    1991   663.1 1992.27   692.4 1998.86
#Mann= 8 ,-1 , 0
       0      .1       0  120.03      .1       0  191.74     .05       0
  277.42      .1       0   314.4    .045       0   345.4      .1       0
  366.99     .06       0  491.36     .05       0
#XS Ineff= 2 , 0
                          377.91         1980.08
Permanent Ineff=
       F       F
Bank Sta=314.4,345.4
XS Rating Curve= 0 ,0
Exp/Cntr=0.5,0.3

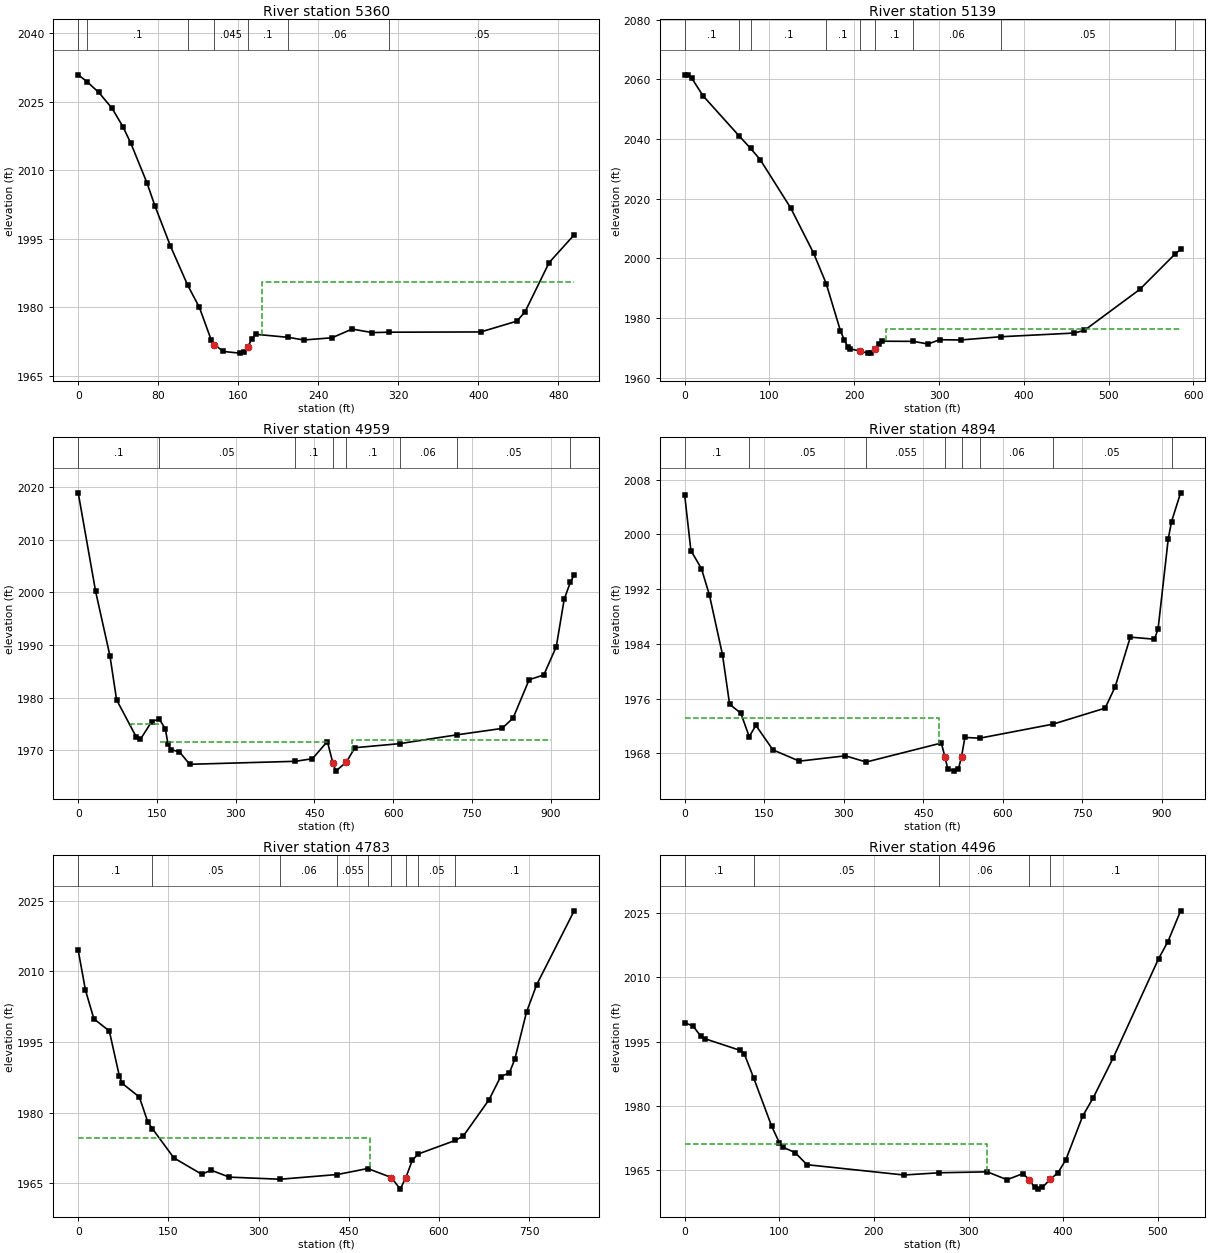
Type RM Length L Ch R = 1 ,5360    ,232,220.5,211.7
XS GIS Cut Line= 2
2454919.20078193549514.4201590192454870.12419128550007.769043944
#Sta/Elev= 30
       0 2030.94    8.722029.458    20.6 2027.07    33.8 2023.62    44.7 2019.58
    52.7 2015.91    68.8 2007.23    76.8 2002.16    92.2 1993.44  109.451984.838
   121.1 1980.01   133.1 1972.77   136.1 1971.84   145.2 1970.33   161.3 1969.97
   165.3 1970.15   169.6  1971.3   173.3 1973.03   177.3  1974.1  210.191973.421
   225.6 1972.85   253.7 1973.33   273.8 1975.24   293.9 1974.47  310.931974.553
   402.4 1974.61   438.6 1976.98   446.7 1979.02   470.8 1989.81   495.8 1995.88
#Mann= 7 ,-1 , 0
       0      .1       0    8.72      .1       0  109.45      .1       0
   136.1    .045       0   169.6      .1       0  210.19     .06       0
  310.93     .05       0
#XS Ineff= 2 , 0
                          183.69         1985.46
Permanent Ineff=
       F       F
Bank Sta=136.1,169.6
XS Rating Curve= 0 ,0
Exp/Cntr(USF)=0,0
Exp/Cntr=0.3,0.1

Type RM Length L Ch R = 1 ,5139    ,195.9,180.8,153.3
XS GIS Cut Line= 2
2454595.18391621549511.7163362552454863.08685637 550031.64177801
#Sta/Elev= 30
       0 2061.38     3.6  2061.5     8.1 2060.49    21.6 2054.48   64.13 2041.05
   77.722036.845    89.1 2033.07   125.1 2016.84   152.1  2001.7  166.931991.503
   183.6 1975.81   188.1 1972.71   192.6 1970.23   195.1 1969.68   206.9 1968.91
   215.8 1968.23   219.6 1968.25   224.8 1969.58   228.6 1971.23   233.1 1972.22
  269.731972.174   287.1 1971.28   300.6 1972.72   325.7 1972.64  372.531973.718
   459.4 1974.96   471.5 1975.87   536.6 1989.56  578.132001.379   584.9 2003.03
#Mann= 9 ,-1 , 0
       0      .1       0   64.13      .1       0   77.72      .1       0
  166.93      .1       0   206.9    .045       0   224.8      .1       0
  269.73     .06       0  372.53     .05       0  578.13      .1       0
#XS Ineff= 2 , 0
                          237.13         1976.24
Permanent Ineff=
       F       F
Bank Sta=206.9,224.8
XS Rating Curve= 0 ,0
Exp/Cntr=0.5,0.3

Type RM Length L Ch R = 1 ,4959    ,69.5,64.8,66.7
XS GIS Cut Line= 4
 2454184.2995865549502.7938204592454419.73200543549789.055892276
2454654.88680352549757.4743114032454846.54870077550034.464909674
#Sta/Elev= 30
       0  2018.9    33.1 2000.19    60.5 1987.89    73.1 1979.56   110.9 1972.44
   118.3 1972.03     140 1975.42  154.191975.905   165.9 1974.06     171 1971.19
   176.2 1970.12   192.8 1969.66   212.5 1967.31  413.691967.875   446.2 1968.37
   474.6 1971.64     485 1967.59   490.7 1966.01   510.9 1967.74     527 1970.46
  612.221971.231  720.591972.896   807.2 1974.12   828.5 1976.11   858.9 1983.38
   886.9 1984.29   910.7 1989.68   925.8  1998.7  937.342001.867   944.7 2003.32
#Mann= 8 ,-1 , 0
       0      .1       0  154.19     .05       0  413.69      .1       0
     485    .045       0   510.9      .1       0  612.22     .06       0
  720.59     .05       0  937.34      .1       0
#XS Ineff= 3 ,-1
     100     155    1975     155     475  1971.5     522     900    1972
Permanent Ineff=
       F       F       F
Bank Sta=485,510.9
XS Rating Curve= 0 ,0
Exp/Cntr=0.5,0.3

Type RM Length L Ch R = 1 ,4894    ,95.2,111.3,123.6
XS GIS Cut Line= 4
2454176.13440696 549529.490808492454414.92452665549849.761502714
2454659.19176761549816.3088206582454837.11940153   550044.406173
#Sta/Elev= 30
       0 2005.77    11.7 1997.64    31.7 1994.98    46.7 1991.12    71.3 1982.41
    84.7 1975.16   105.8 1973.86  121.711970.427   134.3 1972.07   166.4 1968.49
   216.3 1966.84     303 1967.62  342.381966.712   484.1 1969.49   490.7 1967.47
   496.2 1965.71   508.2 1965.38   516.4 1965.74   522.11967.494   528.5 1970.31
  556.351970.197  694.821972.256   792.9 1974.59   811.7 1977.68   840.4 1984.98
   885.9 1984.67   892.8 1986.19     912 1999.36  918.112001.859   935.3 2006.08
#Mann= 8 ,-1 , 0
       0      .1       0  121.71     .05       0  342.38    .055       0
   490.7    .045       0   522.1    .055       0  556.35     .06       0
  694.82     .05       0  918.11      .1       0
#XS Ineff= 2 , 0
           479.4 1973.14
Permanent Ineff=
       F       F
Bank Sta=490.7,522.1
XS Rating Curve= 0 ,0
Exp/Cntr=0.5,0.3

Type RM Length L Ch R = 1 ,4783    ,271.4,286.7,295.5
XS GIS Cut Line= 3
2454117.68159847549532.7458803062454294.70480784549816.308820658
2454704.96356479550085.016106612
#Sta/Elev= 30
       0 2014.49      12 2006.03    26.1 1999.91    51.7 1997.34    68.5 1987.72
    73.3 1986.18   101.6 1983.31   115.7    1978  123.261976.584   159.1 1970.35
   205.3 1966.89   221.1 1967.74   251.3 1966.27  335.811965.823  431.141966.828
  481.411968.098   520.8 1966.19   535.5 1963.72   544.7 1966.14   555.8 1969.93
  565.711971.201  627.021974.073   640.4 1975.01   683.4 1982.77   702.5 1987.64
   716.9 1988.42   725.9 1991.29   745.5 2001.37   762.4 2007.18   824.7 2022.88
#Mann= 9 ,-1 , 0
       0      .1       0  123.26     .05       0  335.81     .06       0
  431.14    .055       0  481.41      .1       0   520.8    .045       0
   544.7      .1       0  565.71     .05       0  627.02      .1       0
#XS Ineff= 2 , 0
          484.66 1974.68
Permanent Ineff=
       F       F
Bank Sta=520.8,544.7
XS Rating Curve= 0 ,0
Exp/Cntr=0.3,0.1

Type RM Length L Ch R = 1 ,4496    ,263.1,265.7,267.5
XS GIS Cut Line= 2
2454090.77291621549578.2616169792454228.87218065550083.830262214
#Sta/Elev= 30
       0  1999.4     8.9 1998.62    17.2  1996.2    21.4 1995.66      58 1992.99
    62.9 1992.19   72.95 1986.47    91.9 1975.24   100.2 1971.28   104.3 1970.28
   116.8 1969.04   129.2 1966.23   231.7 1963.82  269.251964.344   319.7 1964.56
   340.7 1962.72   357.3 1964.14   364.2 1962.75   369.7 1960.94   373.8 1960.52
     378 1960.91   386.3 1962.81   394.6 1964.37   402.9 1967.43   420.6 1977.59
   431.9 1981.93   452.6 1991.07   500.8 2014.36   510.7 2018.36   524.1 2025.55
#Mann= 5 ,-1 , 0
       0      .1       0   72.95     .05       0  269.25     .06       0
   364.2    .045       0   386.3      .1       0
#XS Ineff= 2 , 0
          319.19 1970.98
Permanent Ineff=
       F       F
Bank Sta=364.2,386.3
XS Rating Curve= 0 ,0
Exp/Cntr=0.3,0.1

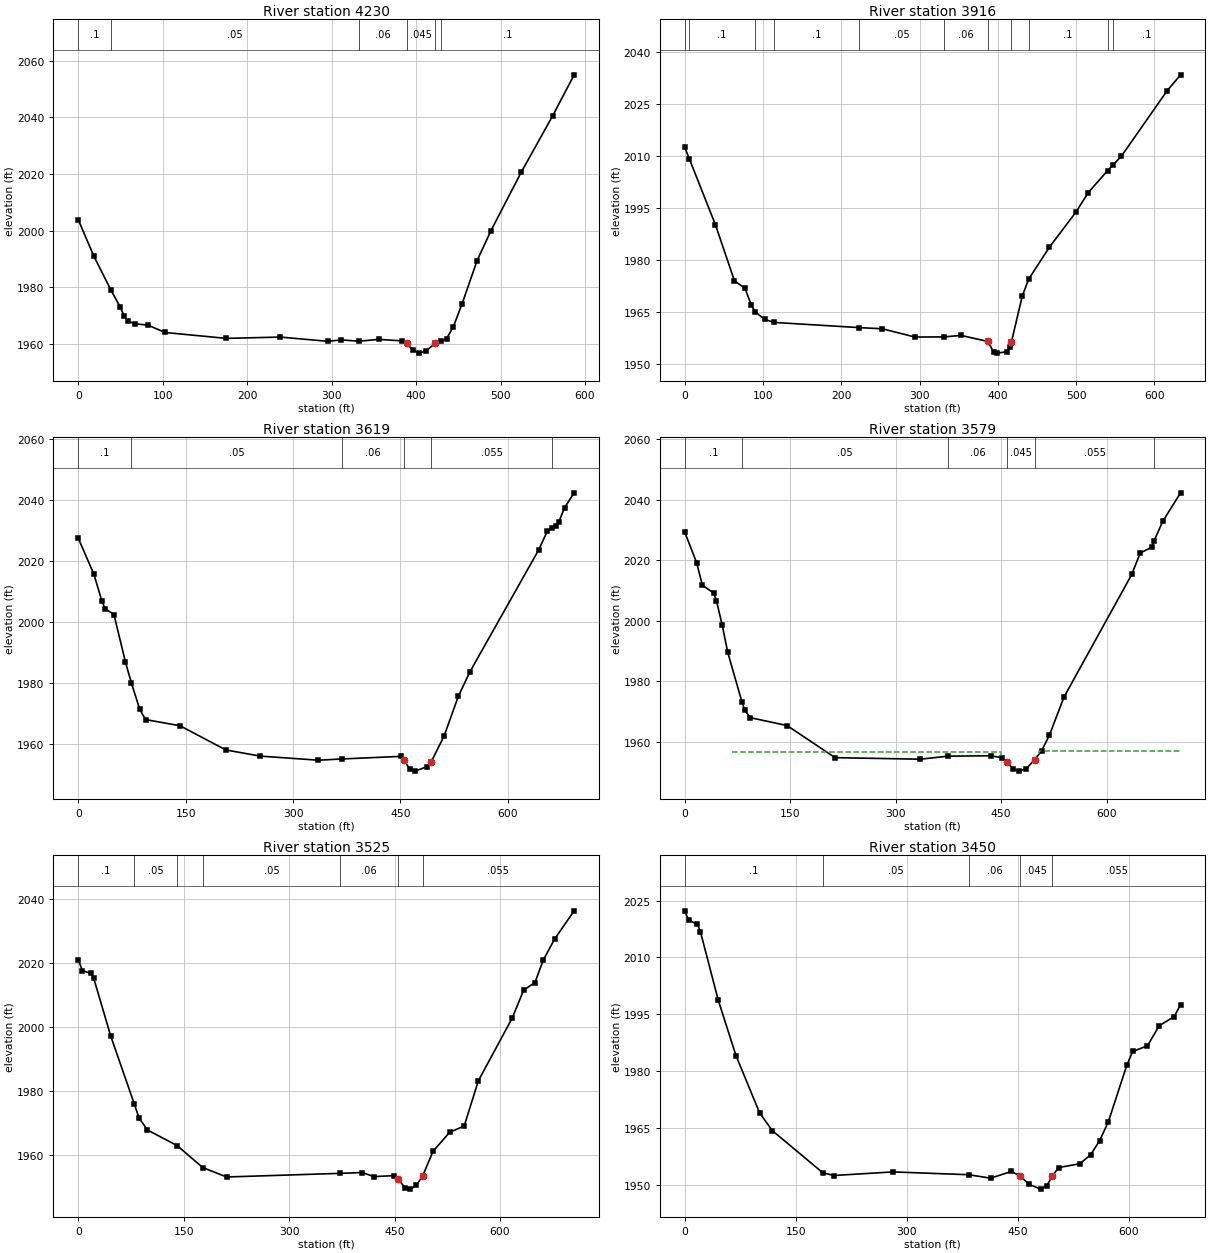
Type RM Length L Ch R = 1 ,4230    ,306.8,314.4,323.1
XS GIS Cut Line= 2
2453893.66196409549544.4419162142453943.63219151550129.379891163
#Sta/Elev= 30
       0 2003.93    18.5 1991.03   38.731979.044    49.8 1973.01    54.6 1969.78
    58.7 1968.12    66.7 1967.16    82.7 1966.65   102.8 1964.06   175.1 1961.98
   239.3 1962.44   295.5 1960.94   311.6 1961.45     3321960.973   355.7 1961.62
   383.4  1961.1   388.7 1960.38   395.9 1957.77   403.9 1956.77   411.9 1957.58
   422.9 1960.27  429.761960.934   436.1 1961.93   444.1 1966.09   454.5 1974.25
   472.2 1989.44   488.2 1999.79   524.4 2020.64   561.8 2040.67   587.1 2055.06
#Mann= 6 ,-1 , 0
       0      .1       0   38.73     .05       0     332     .06       0
   388.7    .045       0   422.9     .06       0  429.76      .1       0
Bank Sta=388.7,422.9
XS Rating Curve= 0 ,0
Exp/Cntr=0.3,0.1

Type RM Length L Ch R = 1 ,3916    ,303.6,296.9,288.2
XS GIS Cut Line= 2
2453752.55294015549501.281928184 2453567.6824135550107.243424357
#Sta/Elev= 30
       0 2012.53    6.012009.104    39.3 1990.15    63.6 1973.99      77 1971.86
    85.3 1966.92   89.941965.117   102.1 1962.88  114.331962.027  222.651960.535
   252.5 1960.19   294.3 1957.81  330.971957.854     353 1958.28   387.3 1956.54
   394.8 1953.41     399 1953.18   411.5 1953.59   415.7 1954.96   417.4 1956.41
   431.1  1969.5  439.291974.457   465.9  1983.7   499.7 1993.78   515.4 1999.38
  540.222005.764  547.612007.474   557.9 2009.94   616.4 2028.79   633.5 2033.34
#Mann= 11 ,-1 , 0
       0      .1       0    6.01      .1       0   89.94     .05       0
  114.33      .1       0  222.65     .05       0  330.97     .06       0
   387.3    .045       0   417.4     .06       0  439.29      .1       0
  540.22      .1       0  547.61      .1       0
Bank Sta=387.3,417.4
XS Rating Curve= 0 ,0
Exp/Cntr=0.3,0.1

Type RM Length L Ch R = 1 ,3619    ,40.1,39.7,38.7
XS GIS Cut Line= 2
   2453315.85644549401.1110418572453360.98177801550092.223472235
#Sta/Elev= 30
       0 2027.48    21.8 2015.69    33.1 2006.83    37.4 2004.37    49.9 2002.41
    65.9 1986.92   74.191980.029      86 1971.31      94    1968   142.1 1965.97
   206.2 1958.03   254.3 1956.01   335.5 1954.67  367.931955.074   450.7 1955.93
   455.21954.688   462.8 1951.77   470.8 1951.09   486.8 1952.57     4931954.151
   510.9 1962.58   530.9 1975.64   546.9 1983.59   643.1 2023.63     655  2029.7
  661.67 2030.87   667.2 2031.33   671.2  2032.8   679.2 2037.45   692.6 2042.32
#Mann= 6 ,-1 , 0
       0      .1       0   74.19     .05       0  367.93     .06       0
   455.2    .045       0     493    .055       0  661.67      .1       0
Bank Sta=455.2,493
XS Rating Curve= 0 ,0
Exp/Cntr=0.5,0.3

Type RM Length L Ch R = 1 ,3579    ,54.8,54.5,54.2
XS GIS Cut Line= 2
2453262.63830342 549401.850189992453328.92889509550104.091474573
#Sta/Elev= 30
       0 2029.38    17.1 2019.14    25.2 2011.77    41.2 2009.17    45.2 2006.59
    53.3 1998.64    61.3  1989.5   81.481973.105    85.4 1970.41    93.5 1967.91
   145.7 1965.31   213.9 1954.69   335.1 1954.18  374.581955.185     435 1955.31
     451  1954.7   458.21953.253   467.3 1950.97   475.1 1950.23   485.7    1951
   498.11954.076   507.7 1956.99   518.7 1962.06   539.4 1974.69   635.9 2015.33
   647.9 2022.38     664 2024.33  667.692026.472   680.2 2032.99   705.4 2042.33
#Mann= 6 ,-1 , 0
       0      .1       0   81.48     .05       0  374.58     .06       0
   458.2    .045       0   498.1    .055       0  667.69      .1       0
#XS Ineff= 2 ,-1
   67.31  450.131956.468  504.55  705.721956.756
Permanent Ineff=
       F       F
Bank Sta=458.2,498.1
XS Rating Curve= 0 ,0
Exp/Cntr=0.5,0.3

Type RM Length L Ch R = 1 ,3525    ,72.3,75,77
XS GIS Cut Line= 2
2453202.43799327 549412.925041142453278.67125322550114.419469896
#Sta/Elev= 30
       0 2021.01       6 2017.54    18.1 2016.69    22.1 2015.16    46.2 1997.23
   79.711976.092    86.5 1971.69    98.5 1967.94  140.731963.093  177.34 1956.22
   211.2 1953.31   372.6 1954.44   404.3  1954.7   420.4 1953.43   448.6 1953.72
   455.31952.707   464.7 1949.94   472.7 1949.53   480.8  1950.7   489.91953.543
   504.9 1961.34   528.3 1967.18   549.2  1969.2   569.3 1983.27   617.6 2002.83
   633.7 2011.47   649.8 2013.84   661.8  2020.9   677.9 2027.42   705.6 2036.17
#Mann= 7 ,-1 , 0
       0      .1       0   79.71     .05       0  140.73      .1       0
  177.34     .05       0   372.6     .06       0   455.3    .045       0
   489.9    .055       0
Bank Sta=455.3,489.9
XS Rating Curve= 0 ,0
Exp/Cntr=0.5,0.3

Type RM Length L Ch R = 1 ,3450    ,170.2,181.5,187.2
XS GIS Cut Line= 2
2453176.99202394549409.5600466072453180.11611538550079.663077245
#Sta/Elev= 30
       0 2022.28     5.3 2019.86    17.3 2018.71    21.3 2016.77    45.3 1998.76
    69.3 1984.11   101.3 1968.97   118.5  1964.3  186.46 1953.23   201.3 1952.48
   281.3 1953.43  383.71 1952.69   413.3 1951.78   441.3 1953.54   453.61952.315
   465.3 1950.13   481.3 1948.89   489.3  1949.8   496.8 1952.36   505.3 1954.57
   534.1  1955.6   548.5 1957.97   560.5  1961.6   572.4 1966.62   597.3 1981.52
   605.3  1985.2   625.3 1986.68   641.3 1992.01   661.3 1994.37   670.1 1997.53
#Mann= 5 ,-1 , 0
       0      .1       0  186.46     .05       0  383.71     .06       0
   453.6    .045       0   496.8    .055       0
Bank Sta=453.6,496.8
XS Rating Curve= 0 ,0
Exp/Cntr=0.3,0.1

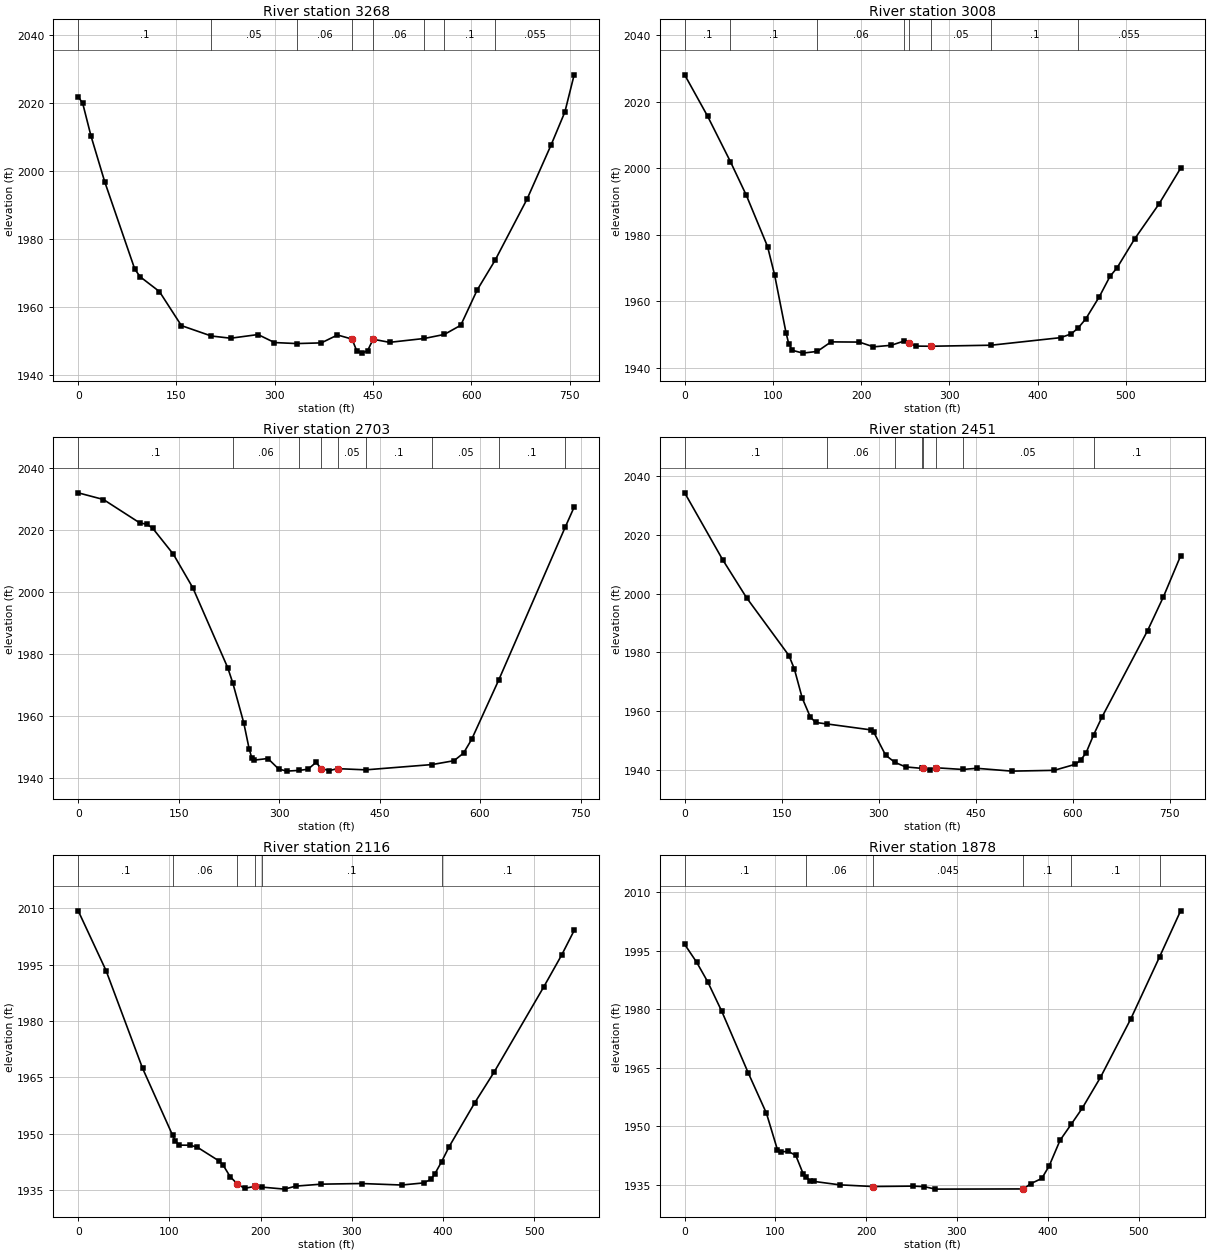
Type RM Length L Ch R = 1 ,3268    ,265.1,260.4,254.5
XS GIS Cut Line= 2
2453143.19250957549416.2559643242452922.57614146550140.491091038
#Sta/Elev= 30
       0 2021.94     6.9 2019.93    19.5 2010.37    40.4 1996.95    86.4  1971.2
    94.7 1968.97     124 1964.64   157.5 1954.64  203.161951.585   232.7 1950.93
   274.5 1952.01   299.6 1949.66  333.531949.359   371.1 1949.56   395.8 1951.88
     4181950.681   425.1 1947.26   433.4 1946.55   441.8 1947.27   450.2 1950.63
   475.3 1949.72  528.05 1950.85  558.861952.038     584 1954.74   609.1 1965.12
  636.35 1973.82   685.2 1991.82     722 2007.78   742.9  2017.4   757.1 2028.34
#Mann= 8 ,-1 , 0
       0      .1       0  203.16     .05       0  333.53     .06       0
     418    .045       0   450.2     .06       0  528.05    .055       0
  558.86      .1       0  636.35    .055       0
Bank Sta=418,450.2
XS Rating Curve= 0 ,0
Exp/Cntr(USF)=0,0
Exp/Cntr=0.3,0.1

Type RM Length L Ch R = 1 ,3008    ,303.4,304.5,304.9
XS GIS Cut Line= 2
2452768.25559016549509.0331637062452775.71426226 550070.96622968
#Sta/Elev= 30
       0 2028.03    25.9 2015.63   51.812001.941    69.9  1991.8    93.9 1976.42
   101.9 1967.88   114.8 1950.57   117.9  1947.2   121.9 1945.23   133.9 1944.37
  150.311944.897   165.9 1947.75   197.9 1947.69   213.9 1946.26   233.9 1946.72
  248.81 1948.02   253.9 1947.56   261.9 1946.48   279.1 1946.44  347.31 1946.75
   425.9 1949.02   437.9 1950.14  445.811951.909   454.4 1954.62   469.9 1961.33
   481.9 1967.42   489.9 1969.99   509.9  1978.7   537.3 1989.13     562 1999.95
#Mann= 8 ,-1 , 0
       0      .1       0   51.81      .1       0  150.31     .06       0
  248.81     .05       0   253.9    .045       0   279.1     .05       0
  347.31      .1       0  445.81    .055       0
Bank Sta=253.9,279.1
XS Rating Curve= 0 ,0
Exp/Cntr=0.3,0.1

Type RM Length L Ch R = 1 ,2703    ,248.5,252.5,255.2
XS GIS Cut Line= 3
2452519.10379413549384.9020453122452479.26241443549467.399535302
2452458.79933743550115.958225362
#Sta/Elev= 30
       0 2031.86    37.7  2029.7    91.6  2022.2     103 2021.67   111.2 2020.44
   142.1 2012.05   171.1 2001.25   223.2 1975.48  230.791970.556   247.2 1957.65
   255.2 1949.32   259.2  1946.3   263.2 1945.66   283.2 1946.17   299.2  1942.8
   311.2  1942.1  330.02 1942.34   343.2 1942.72   355.2 1944.94   362.61942.944
   374.8 1942.27   387.21942.903  429.25 1942.51  528.48 1944.22   561.1 1945.46
   575.3  1947.9   587.4 1952.32  627.72 1971.41  726.952020.685   740.5 2027.26
#Mann= 9 ,-1 , 0
       0      .1       0  230.79     .06       0  330.02     .05       0
   362.6    .045       0   387.2     .05       0  429.25      .1       0
  528.48     .05       0  627.72      .1       0  726.95      .1       0
Bank Sta=362.6,387.2
XS Rating Curve= 0 ,0
Exp/Cntr=0.3,0.1

Type RM Length L Ch R = 1 ,2451    ,336.3,334.3,329.9
XS GIS Cut Line= 2
2452313.55525732549325.6187113432452144.28303102550073.631479536
#Sta/Elev= 30
       0 2034.16    58.7 2011.48    95.6  1998.6   161.2 1978.96   169.5 1974.47
   181.8 1964.51   194.1 1958.19   202.3 1956.25  220.231955.744   288.4 1953.72
   292.5 1952.92   310.7 1945.15  325.111942.712   341.7 1941.17  366.63 1940.68
   368.11940.635   378.6 1940.27   388.21940.887  429.981940.306   451.6  1940.7
   505.7 1939.74   571.4 1940.01   604.2 1942.07   612.1 1943.42   620.6 1945.89
   632.21951.969   645.5 1958.17   715.8 1987.41   740.1 1998.78   766.9 2012.78
#Mann= 8 ,-1 , 0
       0      .1       0  220.23     .06       0  325.11     .05       0
  366.63      .1       0   368.1    .045       0   388.2      .1       0
  429.98     .05       0   632.2      .1       0
Bank Sta=368.1,388.2
XS Rating Curve= 0 ,0
Exp/Cntr=0.3,0.1

Type RM Length L Ch R = 1 ,2116    ,238.7,238.1,285.6
XS GIS Cut Line= 2
2451904.84283597549492.4451799952451919.81378694550035.890885324
#Sta/Elev= 30
       0 2009.28    30.5 1993.41    70.5 1967.47   103.5 1949.62   106.5 1948.15
   110.5 1947.01   122.5 1946.99   130.5 1946.47   154.5 1942.79   158.5 1941.84
   166.5 1938.67   174.5 1936.66   182.5 1935.52   193.31936.047  201.811935.848
   226.2 1935.32   238.5 1936.12   266.5 1936.64   310.6 1936.81   354.6 1936.41
   378.6 1936.97   386.6 1937.91   390.6 1939.22  398.441942.633   406.6 1946.58
   434.6 1958.22     456 1966.44   510.5 1989.12     530 1997.53   543.7 2004.06
#Mann= 6 ,-1 , 0
       0      .1       0   103.5     .06       0   174.5    .045       0
   193.3     .06       0  201.81      .1       0  398.44      .1       0
Bank Sta=174.5,193.3
XS Rating Curve= 0 ,0
Exp/Cntr=0.3,0.1

Type RM Length L Ch R = 1 ,1878    ,515.5,523.3,553.3
XS GIS Cut Line= 2
2451645.34008177549501.801983383     2451725.801550042.276180487
#Sta/Elev= 30
       0  1996.6    13.2 1992.04    25.4 1987.01    40.9 1979.45    69.9 1963.77
    90.1 1953.35   102.2 1944.02   106.2  1943.5   114.3 1943.59   122.4 1942.57
   130.5  1937.9  133.251937.021   138.6 1936.05   142.6 1935.91   170.7 1935.04
   207.3 1934.61   251.8 1934.71     264 1934.58   276.1 1933.94   373.2 1933.99
   381.2 1935.33   393.4 1936.67   401.5 1939.84   413.6 1946.46  425.841950.536
   437.9 1954.61   458.1 1962.56   491.5 1977.53  523.371993.493   546.4  2005.2
#Mann= 6 ,-1 , 0
       0      .1       0  133.25     .06       0   207.3    .045       0
   373.2      .1       0  425.84      .1       0  523.37      .1       0
Bank Sta=207.3,373.2
XS Rating Curve= 0 ,0
Exp/Cntr=0.3,0.1