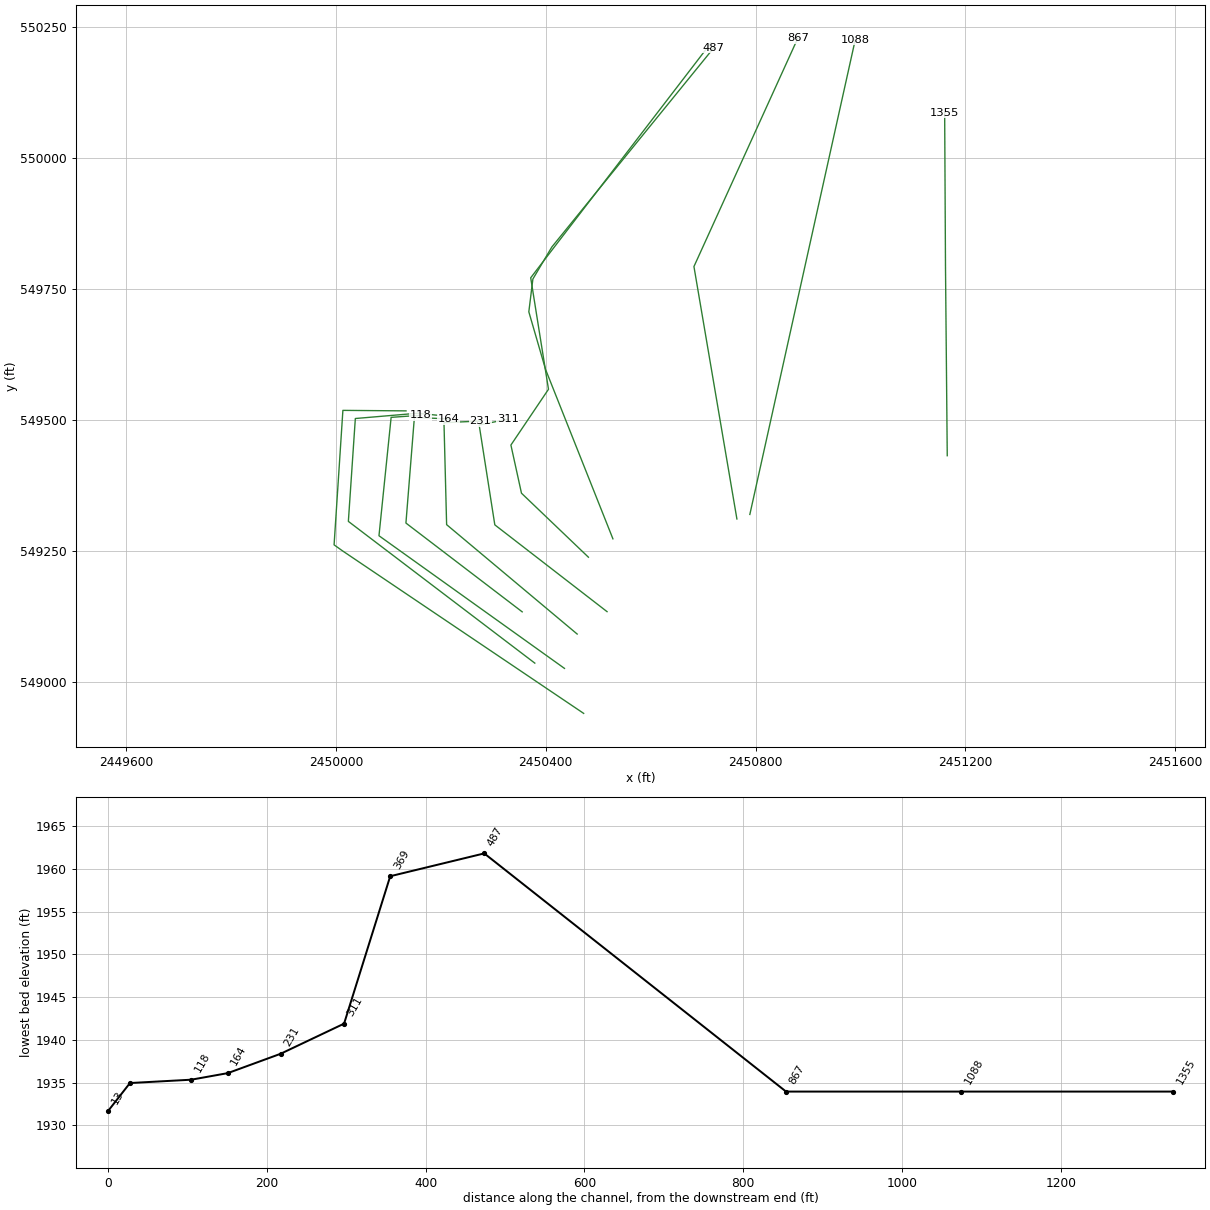
HEC-RAS study LSTONYRN.prj: LSTONYRN

--- LSTONYRN.g01 (geometry) --- (continued)

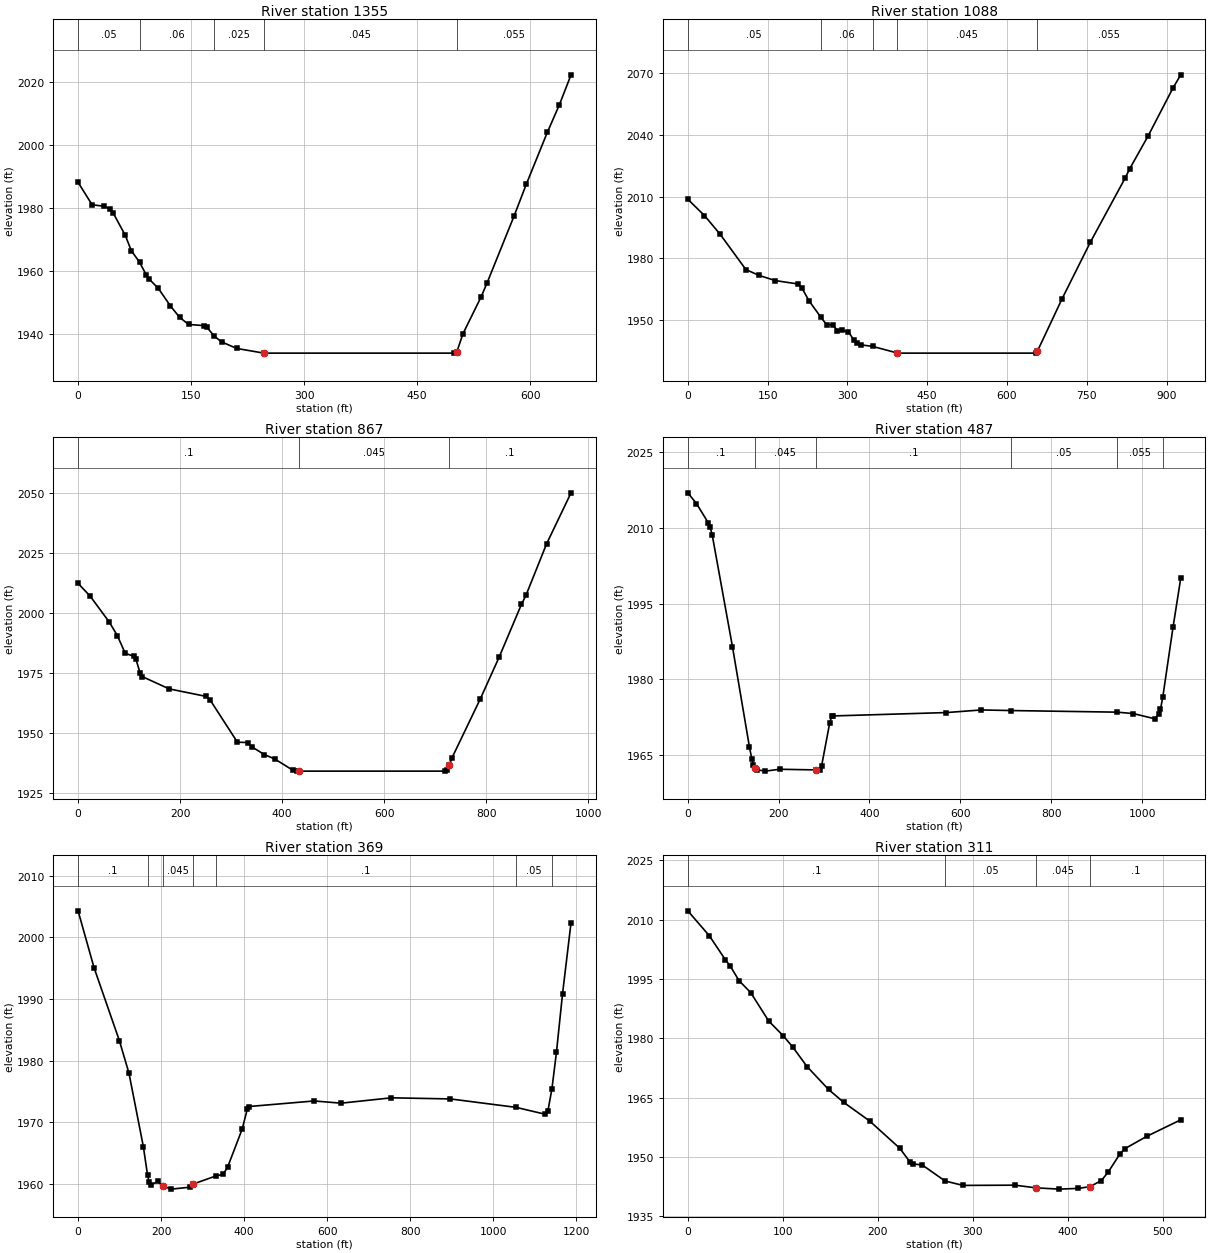
Type RM Length L Ch R = 1 ,1355    ,291.3,267.5,223.6
XS GIS Cut Line= 3
2451165.25781968549432.292524515     2451161.908       549792.13
2451160.33077048550086.418639519
#Sta/Elev= 30
       0 1988.16    18.6 1981.05    34.6 1980.56    42.6 1979.59    46.6 1978.43
    62.6 1971.36    70.6 1966.49   81.651962.771    90.6 1958.74    94.6 1957.38
   106.6 1954.46   122.6 1948.91   134.6 1945.34   146.6 1943.04   167.6 1942.67
   170.6 1942.27   180.51939.366   190.6 1937.49   210.6 1935.42   246.6 1933.94
   498.6 1933.94   502.6 1934.35   510.6 1940.05   534.6 1951.71   542.6 1956.18
   578.6 1977.52   594.6 1987.48   622.6 2004.01   638.6 2012.77   654.1 2022.29
#Mann= 5 ,-1 , 0
       0     .05       0   81.65     .06       0   180.5    .025       0
   246.6    .045       0   502.6    .055       0
Bank Sta=246.6,502.6
XS Rating Curve= 0 ,0
Exp/Cntr=0.3,0.1

Type RM Length L Ch R = 1 ,1088    ,182.3,220.3,147.1
XS GIS Cut Line= 2
2450788.98317287549320.281940246 2450989.8627916550224.874964418
#Sta/Elev= 30
       0 2008.73    31.4 2000.78    60.7 1991.74   109.2 1974.56   133.8 1971.73
   164.6 1969.19   207.5 1967.53   214.9 1965.42     228 1959.29  249.521951.621
   260.8 1947.79   273.1 1947.57   281.3 1944.83   289.5 1945.09   301.8 1944.34
   312.1 1940.31   318.8  1938.9   326.4 1937.93  347.251937.223   392.41934.099
     396 1933.94   654.2 1933.94   657.31934.965   703.3 1960.25   756.6 1987.82
   822.2 2019.08   830.4 2023.45   865.4 2039.56   912.2 2062.91   926.6 2069.19
#Mann= 5 ,-1 , 0
       0     .05       0  249.52     .06       0  347.25    .025       0
   392.4    .045       0   657.3    .055       0
Bank Sta=392.4,657.3
XS Rating Curve= 0 ,0
Exp/Cntr(USF)=0,0
Exp/Cntr=0.3,0.1

Type RM Length L Ch R = 1 ,867     ,382.8,380,694.7
XS GIS Cut Line= 3
2450764.32056521549311.7028610262450682.43638288549792.772432234
2450880.32315685 550227.78215088
#Sta/Elev= 30
       0 2012.43    24.1 2006.96    60.7 1996.38    76.9 1990.62    92.4  1983.2
   109.8 1981.89   113.4 1980.67   121.5 1975.02   125.6 1973.47   178.3 1968.33
   251.3 1965.15   259.4 1963.46   312.2 1946.03   332.5  1945.9   340.6 1944.07
   364.9 1940.87   385.2 1939.04   421.6 1934.23   429.8 1933.94   432.1 1933.94
   718.8 1933.94   723.8 1934.56   727.31936.327   732.6 1939.47   788.3 1964.21
   824.9 1981.52   868.8 2003.68   877.6 2007.43   918.1 2028.99   965.9 2050.26
#Mann= 3 , 0 , 0
       0      .1       0   432.1    .045       0   727.3      .1       0
Bank Sta=432.1,727.3
XS Rating Curve= 0 ,0
Exp/Cntr(USF)=0,0
Exp/Cntr=0.3,0.1

Type RM Length L Ch R = 1 ,487     ,128.6,118.4,11.8
XS GIS Cut Line= 6
 2450527.9989818549273.834264673  2450399.681247549596.556254301
2450367.71896248549706.4924637052450375.44610818549769.012097168
2450411.62319946549830.1267950482450720.35779392550209.810636472
#Sta/Elev= 30
       0 2016.98    19.1 2014.86      45 2011.05    49.3 2010.13    53.7 2008.66
    98.3  1986.5   135.8 1966.56   141.2 1964.13   144.4 1963.04   147.3  1962.5
     153 1962.07   170.3 1961.81   202.5 1962.18   282.3 1962.05   291.3 1962.03
   294.5 1962.81   312.5 1971.39   316.6 1972.64   319.8 1972.75   569.5 1973.42
   646.5 1973.94   711.6 1973.82   945.2  1973.5   980.7 1973.22  1027.6  1972.2
    1037 1973.06  1040.6 1974.04  1045.8 1976.54  1068.3 1990.35  1085.3 2000.08
#Mann= 6 ,-1 , 0
       0      .1       0   147.3    .045       0   282.3      .1       0
   711.6     .05       0   945.2    .055       0  1045.8      .1       0
Bank Sta=147.3,282.3
XS Rating Curve= 0 ,0
Exp/Cntr(USF)=0,0
Exp/Cntr=0.3,0.1

Type RM Length L Ch R = 1 ,369     ,58.1,58.1,58.1
XS GIS Cut Line= 6
2450481.31988714549238.7921190722450353.72488357549360.790850554
2450333.57830406 549452.569712772450405.21058676 549558.89888241
2450371.31054565549771.3726028372450714.73924382550218.870603486
#Sta/Elev= 30
       0 2004.31    38.5 1995.08    99.4 1983.26   122.6 1977.96   157.3 1966.02
   167.3 1961.45   171.3 1960.25   176.5 1959.85   191.6 1960.38   203.9 1959.65
   224.3 1959.14   270.5 1959.46   276.4 1959.94   333.2 1961.31   349.1 1961.53
     360 1962.67   395.2 1968.87   407.9 1972.19     412 1972.55   568.6 1973.45
   633.5 1973.09   754.7 1973.96   896.8 1973.78    1055 1972.41  1124.2 1971.31
  1131.8 1971.89  1141.3 1975.39  1152.2 1981.32  1166.9 1990.84  1187.4  2002.4
#Mann= 7 ,-1 , 0
       0      .1       0   167.3     .05       0   203.9    .045       0
   276.4     .05       0   333.2      .1       0    1055     .05       0
  1141.3      .1       0
Bank Sta=203.9,276.4
XS Rating Curve= 0 ,0
Exp/Cntr(USF)=0,0
Exp/Cntr=0.3,0.1

Type RM Length L Ch R = 1 ,311     ,80,80,80
XS GIS Cut Line= 4
2450516.81344058549135.0490521922450302.91148528549300.449982744
2450273.06470082549490.7232336792450327.78380567549501.915777852
#Sta/Elev= 30
       0 2012.23    22.7 2005.92    39.6 1999.84    44.6 1998.31      54 1994.56
    66.2 1991.57    85.1  1984.4   100.3 1980.68   110.4 1977.83   125.5 1972.87
   148.1 1967.09   164.2  1963.8   191.3 1959.13   223.1 1952.22   233.6 1948.83
   236.8 1948.29   246.9 1947.97   270.8 1943.94   289.7 1942.83   344.3 1942.89
   366.6 1942.21   390.9 1941.89   411.1 1942.08   423.3 1942.52   435.3 1944.07
   442.3 1946.14   454.8 1950.77   459.7 1952.07   483.1 1955.24518.8434 1959.41
#Mann= 4 ,-1 , 0
       0      .1       0   270.8     .05       0   366.6    .045       0
   423.3      .1       0
Bank Sta=366.6,423.3
XS Rating Curve= 0 ,0
Exp/Cntr(USF)=0,0
Exp/Cntr=0.3,0.1

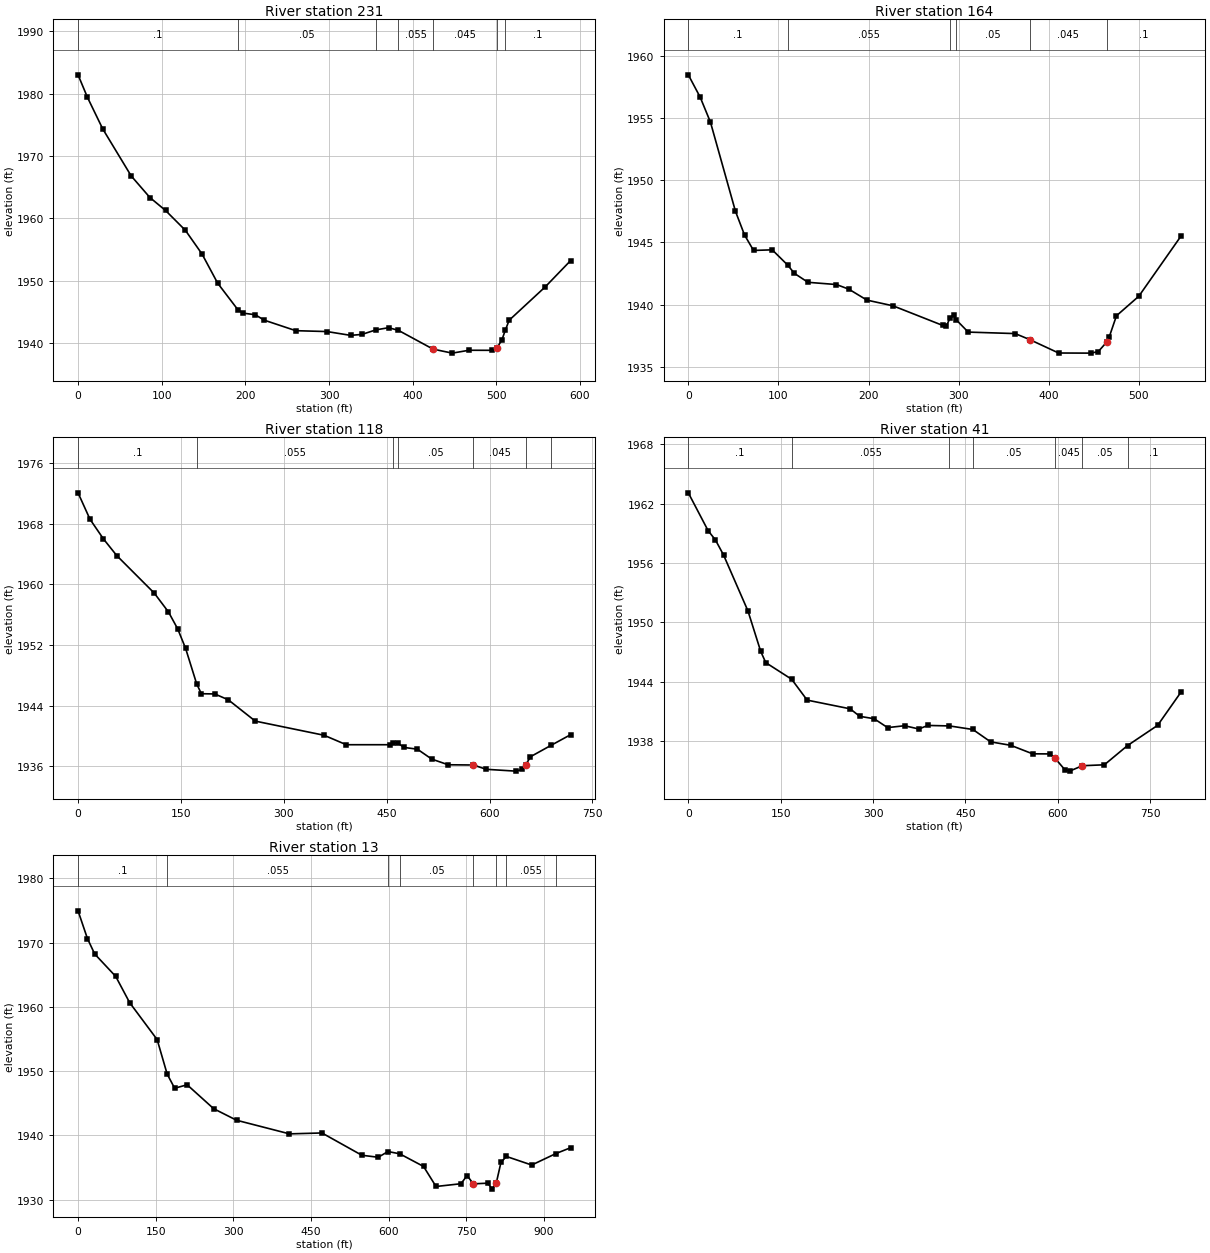
Type RM Length L Ch R = 1 ,231     ,69.6,66.4,57.4
XS GIS Cut Line= 4
2450459.85211296549092.340660325  2450211.041856549300.857758262
2450206.00521112549495.2722505422450275.51091043549498.294237469
#Sta/Elev= 30
       0    1983    11.2  1979.4    29.5 1974.33    63.5 1966.79    85.9 1963.32
   104.6 1961.24   128.3 1958.06   148.2 1954.26   166.9 1949.58   190.9 1945.35
     197 1944.78   211.8 1944.52   222.5 1943.65   260.3 1941.96   297.6 1941.82
   325.8 1941.21   339.3 1941.36     356 1942.09   371.3 1942.44     383 1942.01
   424.4    1939   447.3 1938.36   467.3 1938.82   495.3 1938.81   500.3 1939.14
   506.5 1940.42   510.6 1941.99   515.3 1943.63   558.7 1949.02 588.683 1953.19
#Mann= 7 ,-1 , 0
       0      .1       0   190.9     .05       0     356      .1       0
     383    .055       0   424.4    .045       0   500.3    .055       0
   510.6      .1       0
Bank Sta=424.4,500.3
XS Rating Curve= 0 ,0
Exp/Cntr(USF)=0,0
Exp/Cntr=0.3,0.1

Type RM Length L Ch R = 1 ,164     ,47.5,46.1,37
XS GIS Cut Line= 4
 2450355.0898995549134.6484772982450133.47752488549303.879745189
2450149.59478849549505.345540297 2450215.0711719549502.323553371
#Sta/Elev= 30
       0 1958.46    13.2 1956.66    24.6 1954.65    52.3  1947.5    62.4 1945.59
    72.4 1944.35    93.1  1944.4   110.2 1943.18   117.7 1942.51   132.8 1941.79
   164.4 1941.61   178.1 1941.24   198.2 1940.36   227.2  1939.9   282.5 1938.32
   286.5 1938.29   290.5 1938.94   294.5 1939.16   297.1 1938.79   310.6 1937.79
   362.7 1937.67   378.8 1937.19   410.9 1936.11     447  1936.1     455 1936.23
   464.3 1936.99     467 1937.38   475.1  1939.1   499.9 1940.67546.4947 1945.48
#Mann= 6 ,-1 , 0
       0      .1       0   110.2    .055       0   290.5      .1       0
   297.1     .05       0   378.8    .045       0   464.3      .1       0
Bank Sta=378.8,464.3
XS Rating Curve= 0 ,0
Exp/Cntr(USF)=0,0
Exp/Cntr=0.3,0.1

Type RM Length L Ch R = 1 ,118     ,67.5,77.1,18.2
XS GIS Cut Line= 4
2450435.67621755549026.8642769152450082.10374713549279.703849776
2450105.27231357549505.345540297 2450161.6827362549509.374856199
#Sta/Elev= 30
       0 1972.11    17.4 1968.62    37.1 1966.01    56.5 1963.81   111.2 1958.85
   131.8 1956.37   145.3 1954.13   156.8 1951.56     173 1946.85   179.8 1945.56
   199.3 1945.53     219 1944.76   258.4 1941.94   358.7 1940.07   391.1 1938.82
   454.6 1938.82   458.6  1939.1   466.4 1939.02   475.4 1938.46   494.8 1938.23
   515.7 1936.92   539.7 1936.17   576.2 1936.14   595.3 1935.57   638.2 1935.33
   647.6 1935.55   652.8 1936.15   659.6 1937.23   689.7 1938.74 718.056 1940.14
#Mann= 7 ,-1 , 0
       0      .1       0     173    .055       0   458.6      .1       0
   466.4     .05       0   576.2    .045       0   652.8     .05       0
   689.7      .1       0
Bank Sta=576.2,652.8
XS Rating Curve= 0 ,0
Exp/Cntr(USF)=0,0
Exp/Cntr=0.3,0.1

Type RM Length L Ch R = 1 ,41      ,25.8,27.8,81.7
XS GIS Cut Line= 5
2450379.13969474549036.9105815632450023.75403217549307.076212805
2450037.04219674 549503.140082182450156.04737133549513.257931032
2450193.14615045549509.403512422
#Sta/Elev= 30
       0 1963.08    32.2 1959.25      44 1958.32    57.2  1956.8    96.9 1951.13
   117.6 1947.04   125.8 1945.91   167.8 1944.23     193 1942.12   262.8 1941.24
   278.4 1940.48   301.7 1940.24   323.6 1939.34   351.2 1939.53   374.4  1939.2
   388.9 1939.56   424.1 1939.51   462.1 1939.15   490.9  1937.9   523.6 1937.55
   559.1 1936.69   587.1 1936.68   595.31936.255   611.2  1935.1   619.2 1934.94
   639.81935.486   675.6 1935.58   713.3 1937.53   762.1 1939.57   799.7  1942.9
#Mann= 7 ,-1 , 0
       0      .1       0   167.8    .055       0   424.1      .1       0
   462.1     .05       0   595.3    .045       0   639.8     .05       0
   713.3      .1       0
Bank Sta=595.3,639.8
XS Rating Curve= 0 ,0
Exp/Cntr(USF)=0,0
Exp/Cntr=0.3,0.1

Type RM Length L Ch R = 1 ,13      ,,,
XS GIS Cut Line= 5
2450472.22167718548941.1285340472450012.20811169 549251.16200763
2449996.53854984549262.354551803 2450013.3273661549518.663813357
2450133.64654253549517.716597963
#Sta/Elev= 30
       0 1974.95    18.1 1970.64    32.2 1968.23    72.8 1964.74    99.7 1960.66
   152.8 1954.91   172.1 1949.55   186.6 1947.34   210.7 1947.88   261.9 1944.16
   306.2 1942.36   408.4 1940.24   471.1 1940.38   548.2 1936.91   579.8  1936.6
   598.6 1937.49   621.2 1937.14   667.3 1935.17   691.4 1932.05   739.5 1932.48
   751.5 1933.75   763.5 1932.46   791.6 1932.57   799.6 1931.64   807.6 1932.53
   816.8 1935.79   827.2 1936.73   876.2 1935.39   923.1 1937.18951.1749 1938.08
#Mann= 8 ,-1 , 0
       0      .1       0   172.1    .055       0   598.6      .1       0
   621.2     .05       0   763.5    .045       0   807.6     .05       0
   827.2    .055       0   923.1      .1       0
Bank Sta=763.5,807.6
XS Rating Curve= 0 ,0
Exp/Cntr(USF)=0,0
Exp/Cntr=0.3,0.1
LCMann Table=0

Chan Stop Cuts=-1
Use User Specified Reach Order=0
Composite Channel Slope=5